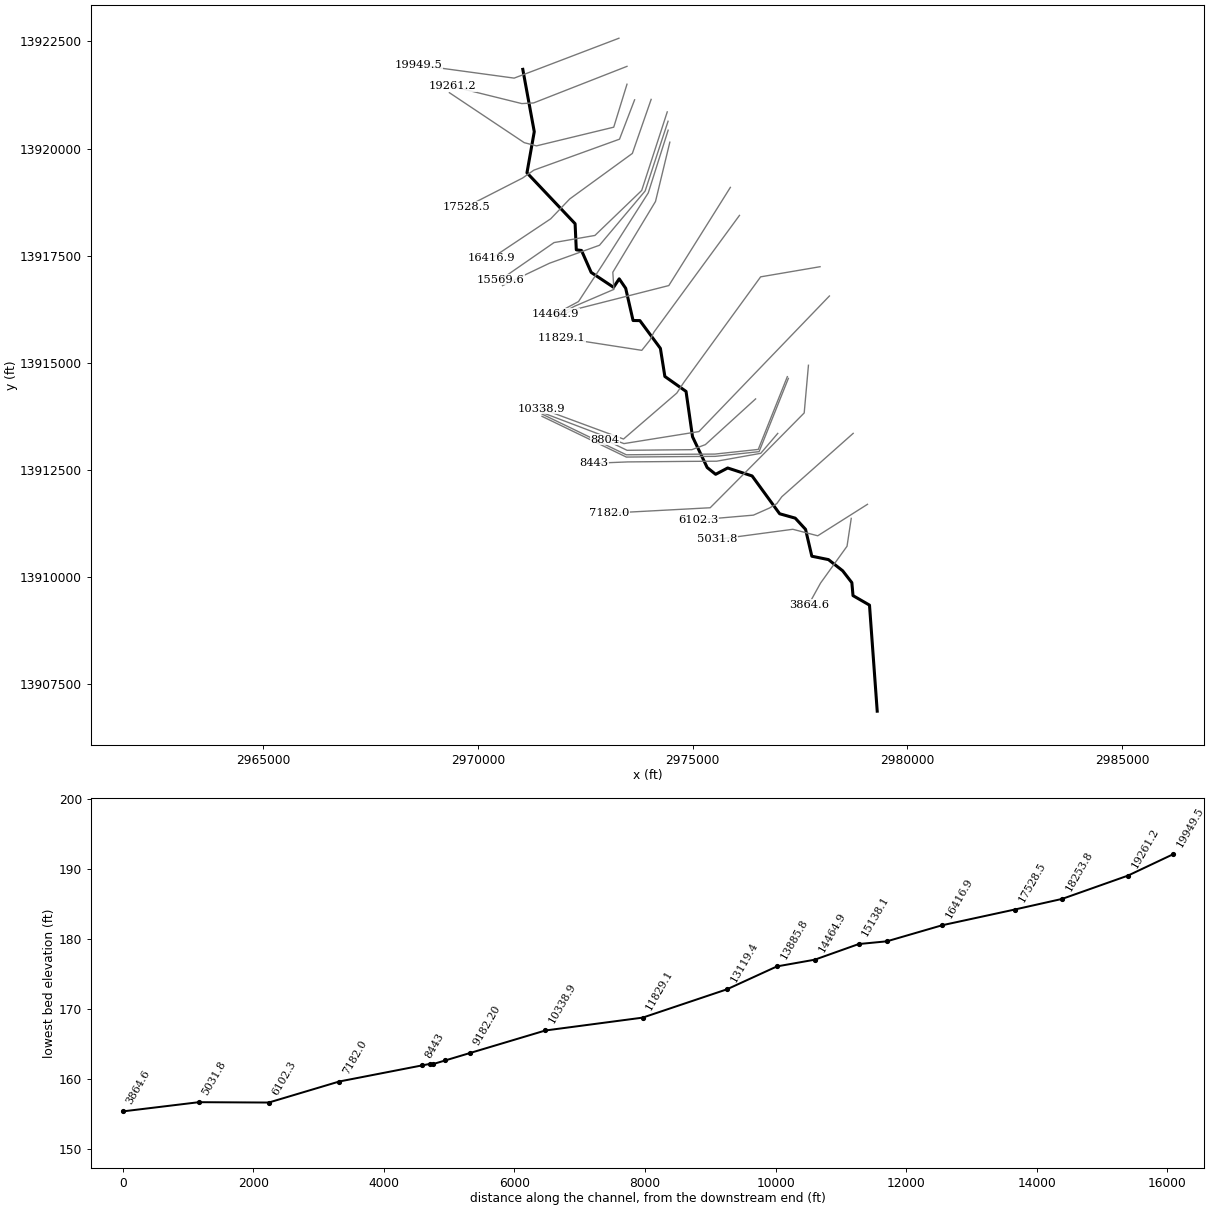
--- K157-00-00.prj (project) ---

Proj Title=K157-00-00
Current Plan=p05
Default Exp/Contr=0.3,0.1
English Units
Geom File=g02
Flow File=f06
Flow File=f05
Plan File=p06
Plan File=p05
Y Axis Title=Elevation
X Axis Title(PF)=Main Channel Distance
X Axis Title(XS)=Station
BEGIN DESCRIPTION:
Cypress Creek Watershed
Wild Cow Gulch
HCFCD Unit K157-00-00
Flood Hazard Model
10, 2, 1, 0.2%
Filename K157-00-00
Prepared by:  Halff Associates, Inc. DATE:  March 26, 2004
Reviewed by:  _________  DATE:  __________________
STATUS (FINAL)
TROPICAL STORM ALLISON RECOVERY PROJECT
END DESCRIPTION:
DSS File=dss
DSS Export Rating Curves= 0
DSS Export Rating Curve Sorted= 0
DSS Export Volume Flow Curves= 0
DXF OffsetX= 0
DXF OffsetY= 0
DXF ScaleX= 1
DXF ScaleY= 10

--- K157-00-00.p05 (plan) ---

Plan Title=Effective MP 2013
Program Version=3.13
Short Identifier=Eff MP 2013
Geom File=g02
Flow File=f05
Subcritical Flow
K Sum by GR= 0
Std Step Tol= 0.01
Critical Tol= 0.01
Num of Std Step Trials= 20
Max Error Tol= 0.3
Flow Tol Ratio= 0.001
Split Flow NTrial= 30
Split Flow Tol= 0.02
Split Flow Ratio= 0.02
Log Output Level= 0
Friction Slope Method= 1
Unsteady Friction Slope Method= 2
Unsteady Bridges Friction Slope Method= 1
Parabolic Critical Depth
Global Vel Dist= 0 , 0 , 0
Global Log Level= 0
CheckData=True
Encroach Param=-1 ,0,0, 0
BEGIN DESCRIPTION:
FEMA Effective MP 2013
At RS 8624.2 ineffective area test elevations lowered to banks due to crossing profiles between the 10-year and 100-year.
END DESCRIPTION:
Computation Interval=1HOUR
Output Interval=1HOUR
Run HTab= 0
Run UNet= 0
Run PostProcess= 0
UNET Theta= 1
UNET Theta Warmup= 1
UNET ZTol= 0.02
UNET ZSATol= 0.1
UNET MxIter= 20
UNET MaxInSteps= 20
UNET DtIC= 0
UNET DtMin= 0
UNET MaxCRTS= 20
UNET WFStab= 2
UNET SFStab= 1
UNET WFX= 1
UNET SFX= 1
UNET DSS MLevel= 4
UNET DZMax Abort= 100
UNET Convert EG Bridges=-1
UNET Use Existing IB Tables=-1
UNET Froude Reduction=False
UNET Froude Limit= 1
UNET Froude Power= 10
Instantaneous Interval=1HOUR
Write IC File= 0
Echo Input=False
Echo Output=False
Write Detailed= 0
Detailed Automatic Start=False, 10

--- K157-00-00.p06 (plan) ---

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Plan Title=Effective FW 2013
Short Identifier=Eff FW 2013
Geom File=g02
Flow File=f06
Encroach Param=-1 ,0,0, 3
Encroach River=K157-00-00
Encroach Reach=K157-00-00_0039
Encroach Node=19949.5
       1  4893.1    5235       1  4893.1 5276.18
Encroach Node=19261.2
       1    4940    5050       1 4942.65 5198.25
Encroach Node=18253.8
       1    4930    5082       1 4861.64  5102.9
Encroach Node=17528.5
       1    4900    5030       1    4731  5104.6
Encroach Node=16416.9
       1    4740    5090       1 4637.04  5104.2
Encroach Node=15569.6
       1    4800    5080       1 4634.31  5107.2
Encroach Node=15138.1
       1    4800    5130       1 4695.94  5068.3
Encroach Node=14464.9
       1    4810    5080       1 4778.44  5104.1
Encroach Node=13885.8
       1    4810  5095.2       1 4785.47  5095.2
Encroach Node=13119.4
       1    4800    5050       1  4785.4    5100
Encroach Node=11829.1
       1    4900    5040       1    4798    5090
Encroach Node=10338.9
       1    4780    5180       1    4700    5200
Encroach Node=9182.20
       1    4800    5150       1    4800    5150
Encroach Node=8804
       1    4780    5150       1    4700    5150
Encroach Node=8624.2
       1 4403.54  5114.2       1 4403.54  5114.2
Encroach Node=8595.2
       0                       1 4303.54  5014.2
Encroach Node=8566.2
       1 4403.54  5114.2       1 4403.54  5114.2
Encroach Node=8443
       1    4400    5065       1    4300    5165
Encroach Node=7182.0
       1    4600    5200       1    4600    5200
Encroach Node=6102.3
       1    4800    5040       1 4702.28 5128.29
Encroach Node=5031.8
       1    4620    5180       1    4550    5250
Encroach Node=3864.6
       1    4725 5482.88       1    4715 5492.88
FEMA Effective FW 2013
DSS File=dss

--- K157-00-00.f05 (steady flow) ---

Flow Title=Effective MP 2013
Program Version=3.13
Number of Profiles= 4
Profile Names=10PCT_10yr,2PCT_50yr,1PCT_100yr,0.2PCT_500yr
River Rch & RM=K157-00-00,K157-00-00_0039       ,19949.5
     292     603     810    1516
River Rch & RM=K157-00-00,K157-00-00_0039       ,19261.2
     295     609     817    1529
River Rch & RM=K157-00-00,K157-00-00_0039       ,18253.8
     298     616     828    1549
River Rch & RM=K157-00-00,K157-00-00_0039       ,17528.5
     299     617     829    1551
River Rch & RM=K157-00-00,K157-00-00_0039       ,16416.9
     235     676     908    1702
River Rch & RM=K157-00-00,K157-00-00_0039       ,15138.1
     335     699     938    1761
River Rch & RM=K157-00-00,K157-00-00_0039       ,13885.8
     340     711     955    1792
River Rch & RM=K157-00-00,K157-00-00_0039       ,13119.4
     379     797    1071    2014
River Rch & RM=K157-00-00,K157-00-00_0039       ,11829.1
     384     810    1088    2047
River Rch & RM=K157-00-00,K157-00-00_0039       ,10338.9
     386     813    1093    2056
River Rch & RM=K157-00-00,K157-00-00_0039       ,8624.2
     395     833    1120    2108
River Rch & RM=K157-00-00,K157-00-00_0039       ,7182.0
     416     882    1186    2233
River Rch & RM=K157-00-00,K157-00-00_0039       ,6102.3
     418     886    1191    2244
River Rch & RM=K157-00-00,K157-00-00_0039       ,5031.8
     528    1139    1533    2901
Boundary for River Rch & Prof#=K157-00-00,K157-00-00_0039       , 1
Up Type= 0
Dn Type= 3
Dn Slope=0.002
Boundary for River Rch & Prof#=K157-00-00,K157-00-00_0039       , 2
Up Type= 0
Dn Type= 3
Dn Slope=0.002
Boundary for River Rch & Prof#=K157-00-00,K157-00-00_0039       , 3
Up Type= 0
Dn Type= 3
Dn Slope=0.002
Boundary for River Rch & Prof#=K157-00-00,K157-00-00_0039       , 4
Up Type= 0
Dn Type= 3
Dn Slope=0.002
DSS Import GetInterval= 0
DSS Import GetPeak= 0
DSS Import FillOption= 0

--- K157-00-00.f06 (steady flow) ---

Flow Title=Effective FW 2013
Program Version=3.13
Number of Profiles= 2
Profile Names=1PCT_100yr,1PCTFloodway_10
River Rch & RM=K157-00-00,K157-00-00_0039       ,19949.5
     810     810
River Rch & RM=K157-00-00,K157-00-00_0039       ,19261.2
     817     817
River Rch & RM=K157-00-00,K157-00-00_0039       ,18253.8
     828     828
River Rch & RM=K157-00-00,K157-00-00_0039       ,17528.5
     829     829
River Rch & RM=K157-00-00,K157-00-00_0039       ,16416.9
     908     908
River Rch & RM=K157-00-00,K157-00-00_0039       ,15138.1
     938     938
River Rch & RM=K157-00-00,K157-00-00_0039       ,13885.8
     955     955
River Rch & RM=K157-00-00,K157-00-00_0039       ,13119.4
    1071    1071
River Rch & RM=K157-00-00,K157-00-00_0039       ,11829.1
    1088    1088
River Rch & RM=K157-00-00,K157-00-00_0039       ,10338.9
    1093    1093
River Rch & RM=K157-00-00,K157-00-00_0039       ,8624.2
    1120    1120
River Rch & RM=K157-00-00,K157-00-00_0039       ,7182.0
    1186    1186
River Rch & RM=K157-00-00,K157-00-00_0039       ,6102.3
    1191    1191
River Rch & RM=K157-00-00,K157-00-00_0039       ,5031.8
    1533    1533
Boundary for River Rch & Prof#=K157-00-00,K157-00-00_0039       , 1
Up Type= 0
Dn Type= 3
Dn Slope=0.002
Boundary for River Rch & Prof#=K157-00-00,K157-00-00_0039       , 2
Up Type= 0
Dn Type= 3
Dn Slope=0.002
DSS Import GetInterval= 0
DSS Import GetPeak= 0
DSS Import FillOption= 0

--- K157-00-00.g02 (geometry) ---

Geom Title=K157-00-00 2013
Program Version=3.13

River Reach=K157-00-00      ,K157-00-00_0039
Reach XY= 30
      2971047.64     13921849.03       2971314.5       13920395.
       2971144.6     13919435.44      2972265.31     13918248.21
      2972293.08     13917638.83       2972414.1     13917623.72
      2972640.31     13917111.06      2973160.77     13916764.11
      2973292.21     13916961.75      2973443.26     13916741.26
      2973615.13     13915989.53      2973773.99     13915986.92
      2974251.42     13915339.35       2974355.5       13914684.
      2974848.64     13914335.01      2974999.45     13913277.88
      2975340.83     13912558.97      2975537.87     13912400.99
      2975818.26     13912548.56      2976386.95     13912362.77
      2977028.09     13911480.48      2977391.17     13911378.42
      2977631.22     13911116.94      2977777.75       13910490.
       2978164.5       13910411.      2978495.75       13910150.
       2978709.5       13909873.      2978736.25       13909571.
      2979120.25       13909349.        2979300.     13906874.59

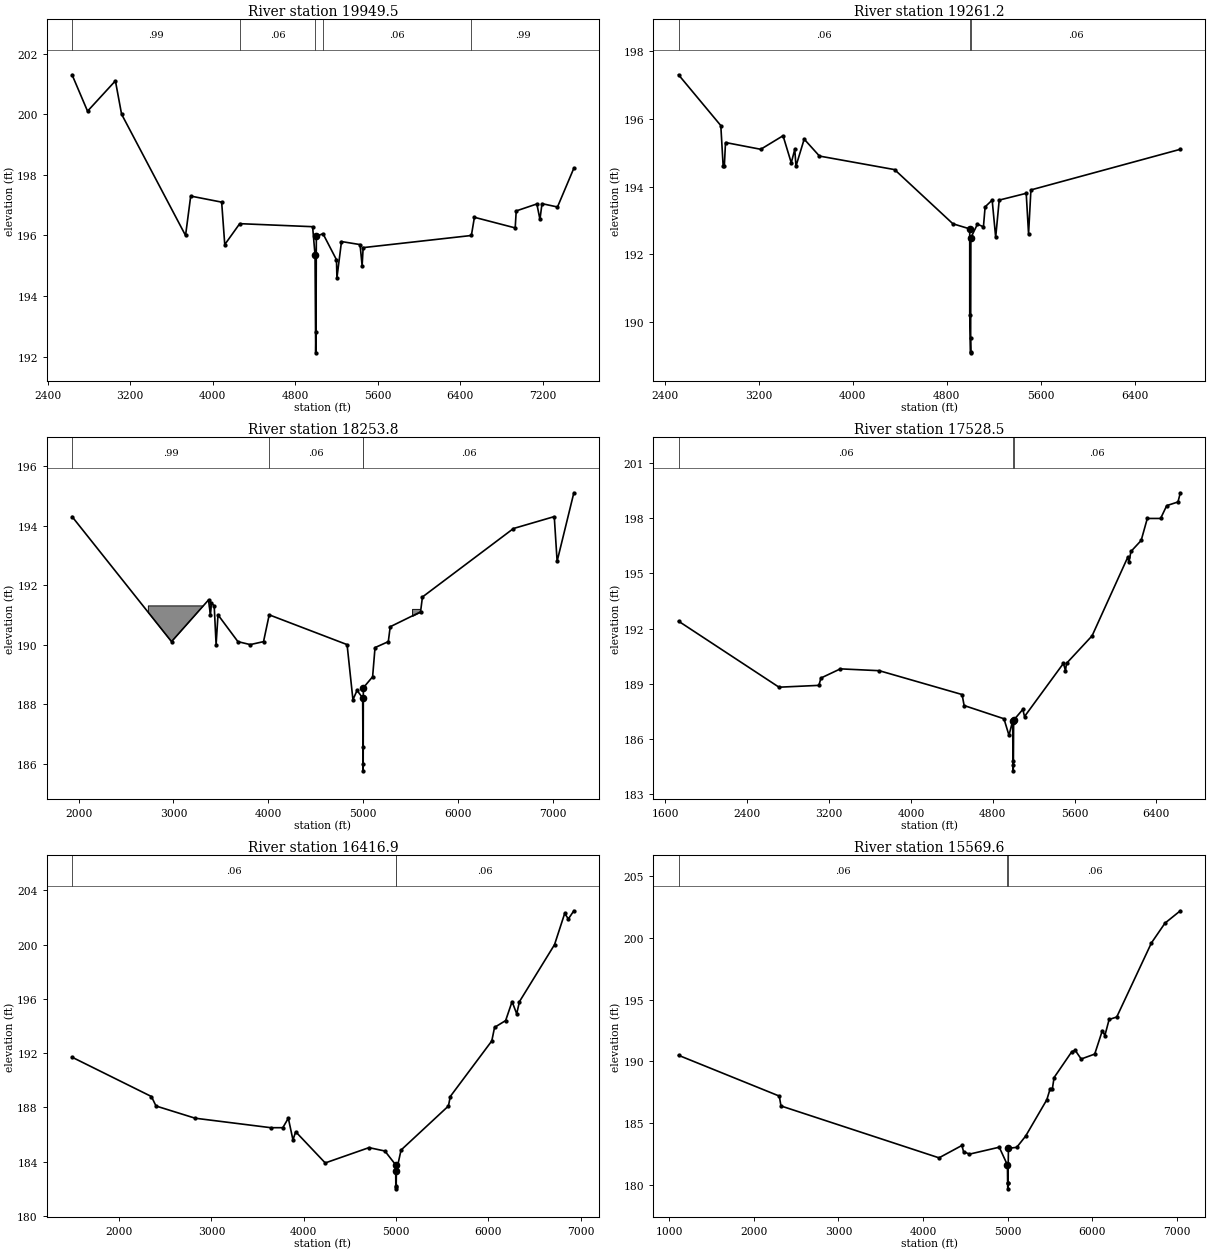
Type RM Length L Ch R = 1 ,19949.5 ,769,688.3,624
BEGIN DESCRIPTION:
Cross Section K157-00-00-X11
END DESCRIPTION:
XS GIS Cut Line= 6
      2973286.07     13922575.43      2971336.17     13921830.65
      2970845.93      13921644.9      2969598.57     13921815.01
 2969519.799132313921825.7524579 2968614.281040513921949.2434169
#Sta/Elev= 30
    2638   201.3    2788   200.1    3058   201.1    3118     200    3738     196
    3788   197.3    4088   197.1    4118   195.7    4263  196.39  4969.6  196.29
  4993.1  195.36  4999.4  192.13  5002.7  192.83  5005.7  195.97    5070  196.06
  5200.9   195.2  5205.3   194.6  5249.5   195.8  5429.5   195.7  5449.5     195
  5459.5   195.6  6508.5     196    6538   196.6  6933.2  196.25  6943.2  196.81
  7143.2  197.04  7173.2  196.53  7193.2  197.05  7343.2  196.94  7501.9  198.22
#Mann= 5 ,-1 , 0
    2638     .99       0    4263     .06       0  4993.1     .07       0
    5070     .06       0  6508.5     .99       0
Bank Sta=4993.1,5005.7
Exp/Cntr=0.3,0.1

Type RM Length L Ch R = 1 ,19261.2 ,1067,1007.4,929
BEGIN DESCRIPTION:
Cross Section K157-00-00-X10
END DESCRIPTION:
XS GIS Cut Line= 4
      2973473.57     13921919.18      2971298.47     13921065.53
      2971024.67     13921050.52      2969411.07     13921450.43
#Sta/Elev= 30
  2516.2   197.3  2876.2   195.8  2896.2   194.6  2906.2   194.6  2916.2   195.3
  3216.2   195.1  3406.2   195.5  3476.2   194.7  3506.2   195.1  3516.2   194.6
  3586.2   195.4  3716.2   194.9  4356.2   194.5  4852.8   192.9    4996  192.75
  4996.2   190.2  5003.2  189.11  5003.7  189.09  5003.8  189.52  5005.8  192.49
  5061.8  192.89  5112.7  192.81    5127   193.4    5187   193.6    5217   192.5
    5247   193.6    5477   193.8    5497   192.6    5517   193.9  6789.4   195.1
#Mann= 3 ,-1 , 0
  2516.2     .06       0    4996     .07       0  5005.8     .06       0
Bank Sta=4996,5005.8
Exp/Cntr=0.3,0.1

Type RM Length L Ch R = 1 ,18253.8 ,574,725.3,799
BEGIN DESCRIPTION:
Cross Section K157-00-00-X09
END DESCRIPTION:
XS GIS Cut Line= 5
      2973473.57     13921502.51      2973164.97     13920500.17
      2971365.98     13920064.09      2971080.93      13920139.1
      2969338.16      13921304.6
#Sta/Elev= 30
  1931.5   194.3  2980.3   190.1  3370.3   191.5  3390.3     191  3400.3   191.4
  3430.3   191.3  3450.3     190  3470.3     191  3680.3   190.1  3810.3     190
  3950.3   190.1  4010.3     191  4831.4     190  4893.1  188.15  4936.6  188.46
  4995.8  188.21  4998.6  186.55  4998.7  185.98  5001.1  185.76  5002.9  188.55
  5100.6  188.92  5126.1   189.9  5266.1   190.1  5286.1   190.6  5606.1   191.1
  5626.1   191.6  6586.1   193.9  7016.1   194.3  7046.1   192.8  7222.7   195.1
#Mann= 4 ,-1 , 0
  1931.5     .99       0  4010.3     .06       0  4995.8     .07       0
  5002.9     .06       0
#Block Obstruct= 2 ,-1
    2736    3402   191.3 5516.85    5600   191.2
Bank Sta=4995.8,5002.9
Exp/Cntr=0.3,0.1

Type RM Length L Ch R = 1 ,17528.5 ,1062,1111.6,1131
BEGIN DESCRIPTION:
Cross Section K157-00-00-X08
END DESCRIPTION:
XS GIS Cut Line= 5
      2973650.66     13921137.93      2973299.53     13920220.37
      2971305.97     13919497.74      2971043.42     13919313.95
      2969723.57     13918637.93
#Sta/Elev= 30
  1728.1   192.4  2710.5   188.8  3100.5   188.9  3120.5   189.3  3310.5   189.8
  3690.5   189.7  4500.5   188.4  4520.5   187.8  4909.9  187.08  4958.9  186.18
  4995.3  186.96  4997.9  184.78  5000.1  184.24  5002.1  184.55  5004.6     187
  5094.2  187.59    5111   187.2  5491.5   190.1  5511.5   189.7  5521.5   190.1
  5771.5   191.6  6121.5   195.9  6131.5   195.6  6151.5   196.2  6251.5   196.8
  6311.5     198  6441.5     198  6501.5   198.7  6611.5   198.9  6634.4   199.4
#Mann= 3 ,-1 , 0
  1728.1     .06       0  4995.3     .07       0  5004.6     .06       0
Bank Sta=4995.3,5004.6
Exp/Cntr=0.3,0.1

Type RM Length L Ch R = 1 ,16416.9 ,1069,847.3,744
BEGIN DESCRIPTION:
Cross Section K157-00-00-X7
END DESCRIPTION:
XS GIS Cut Line= 5
      2974036.07     13921148.35      2973598.57     13919887.93
      2972140.24     13918825.43      2971697.07     13918362.14
      2970317.32     13917440.01
#Sta/Elev= 30
  1488.8   191.7  2348.8   188.8  2398.8   188.1    2823   187.2    3643   186.5
    3773   186.5    3833   187.2    3883   185.6    3913   186.2    4233   183.9
  4707.5  185.03  4879.6  184.78  4996.4  183.76  4998.1  182.22  4999.3  181.99
    5002  182.11  5004.2  183.27  5054.7  184.85  5568.4   188.1  5588.4   188.8
  6038.4   192.9  6068.4   193.9  6188.4   194.4  6258.4   195.8  6308.4   194.9
  6338.4   195.8  6718.4     200  6828.4   202.3  6868.4   201.9    6928   202.5
#Mann= 3 ,-1 , 0
  1488.8     .06       0  4996.4     .07       0  5004.2     .06       0
Bank Sta=4996.4,5004.2
Exp/Cntr=0.3,0.1

Type RM Length L Ch R = 1 ,15569.6 ,225,431.5,388
BEGIN DESCRIPTION:
Cross Section K157-00-00-X6
END DESCRIPTION:
XS GIS Cut Line= 5
      2974411.07     13920856.68      2973816.28     13919024.04
      2972726.73     13917974.07      2971775.13      13917807.7
      2970525.66     13916940.01
#Sta/Elev= 30
  1110.5   190.5  2300.6   187.2  2320.6   186.4  4187.3   182.2  4457.3   183.2
  4477.3   182.7  4547.3   182.5  4898.9  183.06  4995.5  181.62  4997.8  180.15
  4999.7  179.69  5002.3  180.14  5007.2  182.97  5105.3  183.05  5210.5  183.96
  5460.5   186.9  5500.5   187.8  5526.5   187.8  5546.5   188.7  5756.5   190.8
  5796.5   190.9  5866.5   190.2  6026.5   190.6  6116.5   192.5  6146.5   192.1
  6196.5   193.4  6286.5   193.6  6696.5   199.6  6856.5   201.2  7037.7   202.2
#Mann= 3 ,-1 , 0
  1110.5     .06       0  4995.5     .07       0  5007.2     .06       0
Bank Sta=4995.5,5007.2
Exp/Cntr=0.3,0.1

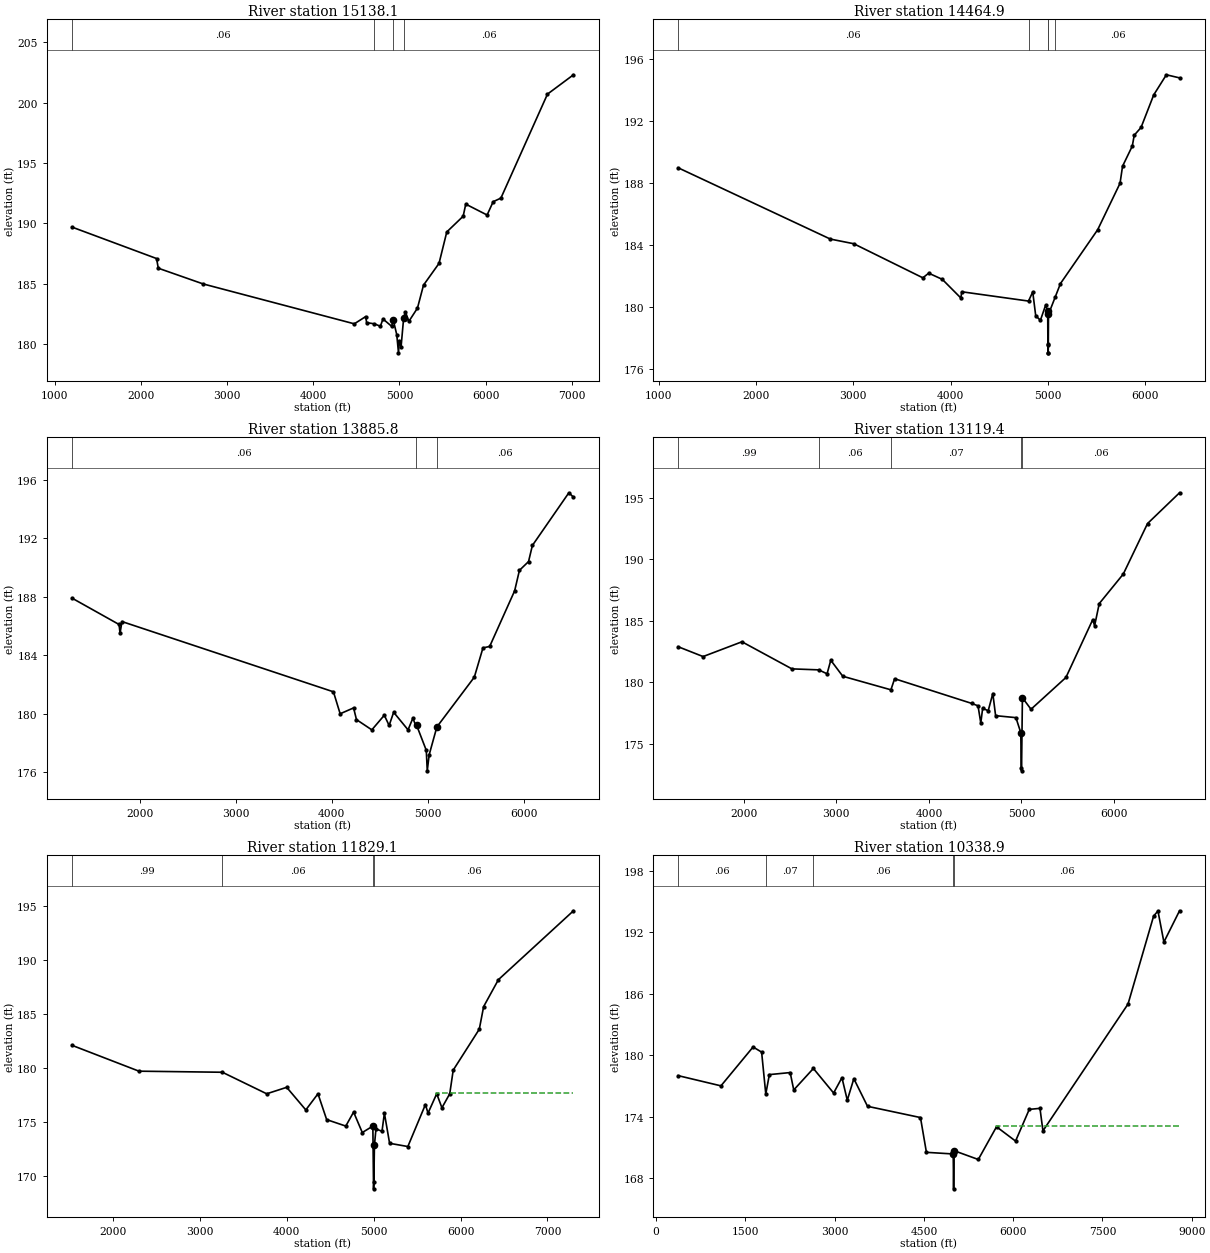
Type RM Length L Ch R = 1 ,15138.1 ,410,673.2,741
BEGIN DESCRIPTION:
Cross Section K157-00-00-X5B
END DESCRIPTION:
XS GIS Cut Line= 5
      2974429.66     13920638.39       2973895.8     13919010.79
      2972833.19     13917745.17      2971668.78     13917325.88
      2970575.49     13916803.75
#Sta/Elev= 30
  1202.9   189.7  2182.9   187.1  2202.9   186.3  2722.9     185  4475.8   181.7
  4608.4   182.3  4618.4   181.8  4708.4   181.7  4778.4   181.5  4808.4   182.1
  4908.4   181.5  4928.3     182  4968.4   180.8  4988.4   179.3  4998.4   180.3
  5018.4   179.8  5048.4   182.2  5068.4   182.7  5108.4   181.9  5208.4     183
  5278.4   184.9  5458.4   186.7  5548.4   189.3  5738.4   190.6  5768.4   191.6
    6016   190.7    6086   191.8    6176   192.1    6716   200.7  7017.5   202.3
#Mann= 4 ,-1 , 0
  1202.9     .06       0  4708.4     .08       0  4928.3     .07       0
  5048.4     .06       0
Bank Sta=4928.3,5048.4
Exp/Cntr=0.3,0.1

Type RM Length L Ch R = 1 ,14464.9 ,295,579.1,580
BEGIN DESCRIPTION:
Cross Section K157-00-00-X5
END DESCRIPTION:
XS GIS Cut Line= 5
      2974431.91      13920429.6      2973969.29     13918967.36
      2972914.79     13917308.86      2972344.89     13916431.99
      2971811.99     13916144.93
#Sta/Elev= 30
  1199.9     189  2763.6   184.4  3003.6   184.1  3713.6   181.9  3773.6   182.2
  3913.6   181.8  4103.6   180.6  4113.6     181  4798.9   180.4  4842.2  180.99
  4872.9  179.45  4921.1  179.16  4974.2  180.13  4995.9  179.77  4997.9  177.65
  4999.2  177.08  5001.1  177.06  5002.1  177.56  5004.1  179.55    5075  180.69
    5127  181.53  5508.9     185  5738.9     188  5764.7   189.1  5864.7   190.4
  5884.7   191.1  5954.7   191.6  6084.7   193.7  6214.7     195    6350   194.8
#Mann= 5 ,-1 , 0
  1199.9     .06       0  4798.9     .08       0  4995.9     .07       0
  5004.1     .08       0    5075     .06       0
Bank Sta=4995.9,5004.1
Exp/Cntr=0.3,0.1

Type RM Length L Ch R = 1 ,13885.8 ,843,766.4,407
BEGIN DESCRIPTION:
Cross Section K157-00-00-X5A
END DESCRIPTION:
XS GIS Cut Line= 6
      2974471.16     13920150.11       2974137.5     13918766.65
      2973143.47     13917115.33      2973169.08     13916715.86
      2972255.06     13916323.06      2971833.96     13916096.62
#Sta/Elev= 30
  1294.5   187.9  1784.5   186.1  1794.5   185.5  1814.5   186.3  4017.6   181.5
  4087.6     180  4227.6   180.4  4257.6   179.6  4417.6   178.9  4547.6   179.9
  4597.6   179.2    4645   180.1    4795   178.9    4845   179.7    4875   179.2
  4884.9   179.2    4985   177.5    4995   176.1    5015   177.2  5095.2   179.1
  5095.3   179.1  5485.3   182.5  5575.3   184.5  5645.3   184.6  5905.3   188.4
  5955.3   189.8  6050.2   190.4  6090.2   191.5  6470.2   195.1  6518.3   194.8
#Mann= 3 ,-1 , 0
  1294.5     .06       0    4875     .07       0  5095.3     .06       0
Bank Sta=4884.9,5095.2
Exp/Cntr=0.3,0.1

Type RM Length L Ch R = 1 ,13119.4 ,950,1290.3,1287
BEGIN DESCRIPTION:
Cross Section K157-00-00-X04
END DESCRIPTION:
XS GIS Cut Line= 4
      2975880.23     13919095.17      2974447.47     13916804.89
       2972187.6     13916229.39      2971851.53     13916039.51
#Sta/Elev= 30
  1289.5   182.9  1559.5   182.1  1979.5   183.3  2519.5   181.1  2809.2  181.02
  2899.5   180.7  2939.5   181.8  3069.5   180.5  3589.5   179.4  3629.5   180.3
    4461   178.3    4531   178.1    4561   176.7    4581   177.9    4641   177.7
    4691   179.1    4721   177.3  4940.6  177.14  4993.1  175.92  4998.5  173.06
  5001.3  172.82  5010.7  178.76  5103.6  177.82    5481   180.4    5771   185.1
    5791   184.6    5841   186.4    6101   188.8    6363   192.9    6709   195.4
#Mann= 5 ,-1 , 0
  1289.5     .99       0  2809.2     .06       0  3589.5     .07       0
  4993.1     .08       0  5010.7     .06       0
Bank Sta=4993.1,5010.7
Exp/Cntr=0.3,0.1

Type RM Length L Ch R = 1 ,11829.1 ,1528,1490.2,1426
BEGIN DESCRIPTION:
Cross Section K157-00-00-X3C
END DESCRIPTION:
XS GIS Cut Line= 5
      2976092.28     13918441.36       2974102.4     13915720.78
      2974006.87     13915529.71      2973818.41      13915293.5
      2971956.95     13915582.69
#Sta/Elev= 30
  1528.8   182.1  2298.8   179.7  3258.8   179.6  3768.8   177.6  3998.8   178.2
  4218.8   176.1  4358.8   177.6  4458.8   175.2  4678.8   174.6  4768.8   175.9
  4868.8     174  4990.4   174.6  4998.4  168.77  5002.1  169.37  5008.4  172.81
    5026  174.33  5095.7  174.12  5123.1   175.8  5183.1     173  5393.1   172.7
  5595.2   176.6  5625.2   175.8  5725.2   177.6  5785.2   176.3  5875.2   177.6
  5915.2   179.8  6215.2   183.6  6265.2   185.7  6435.2   188.2    7299   194.6
#Mann= 4 ,-1 , 0
  1528.8     .99       0  3258.8     .06       0  4990.4     .08       0
  5008.4     .06       0
#XS Ineff= 2 , 0
                         5721.49          177.63
Permanent Ineff=
       F       F
#Block Obstruct= 2 , 0
         4749.66  174.98 5134.76          174.98
Bank Sta=4990.4,5008.4
Exp/Cntr=0.3,0.1

Type RM Length L Ch R = 1 ,10338.9 ,1156.7,1156.7,1156.7
BEGIN DESCRIPTION:
Cross Section K157-00-00-X3B
END DESCRIPTION:
XS GIS Cut Line= 6
      2977969.07     13917244.66      2976585.51     13917008.16
      2974793.62     13914540.65      2974633.46     13914296.19
       2973392.7     13913224.08      2971477.01     13913933.59
#Sta/Elev= 30
   368.7     178  1088.7     177  1628.7   180.8  1772.3   180.3  1842.3   176.2
  1902.3   178.1  2252.3   178.3  2312.3   176.6  2642.3   178.7  2982.3   176.3
  3122.3   177.8  3212.3   175.6  3322.3   177.7  3552.3     175  4442.3   173.9
  4542.3   170.5  4992.8  170.34  4999.2  166.93  5007.4  170.66  5414.1   169.8
  5720.5     173  6040.5   171.6  6270.9   174.7  6450.9   174.8  6500.9   172.6
  7930.9     185  8360.9   193.6  8433.9   194.1  8533.9  191.06  8796.7  194.12
#Mann= 5 ,-1 , 0
   368.7     .06       0  1842.3     .07       0  2642.3     .06       0
  4992.8     .07       0  5007.4     .06       0
#XS Ineff= 2 , 0
                         5715.27          173.11
Permanent Ineff=
       F       F
Bank Sta=4992.8,5007.4
Exp/Cntr=0.3,0.1

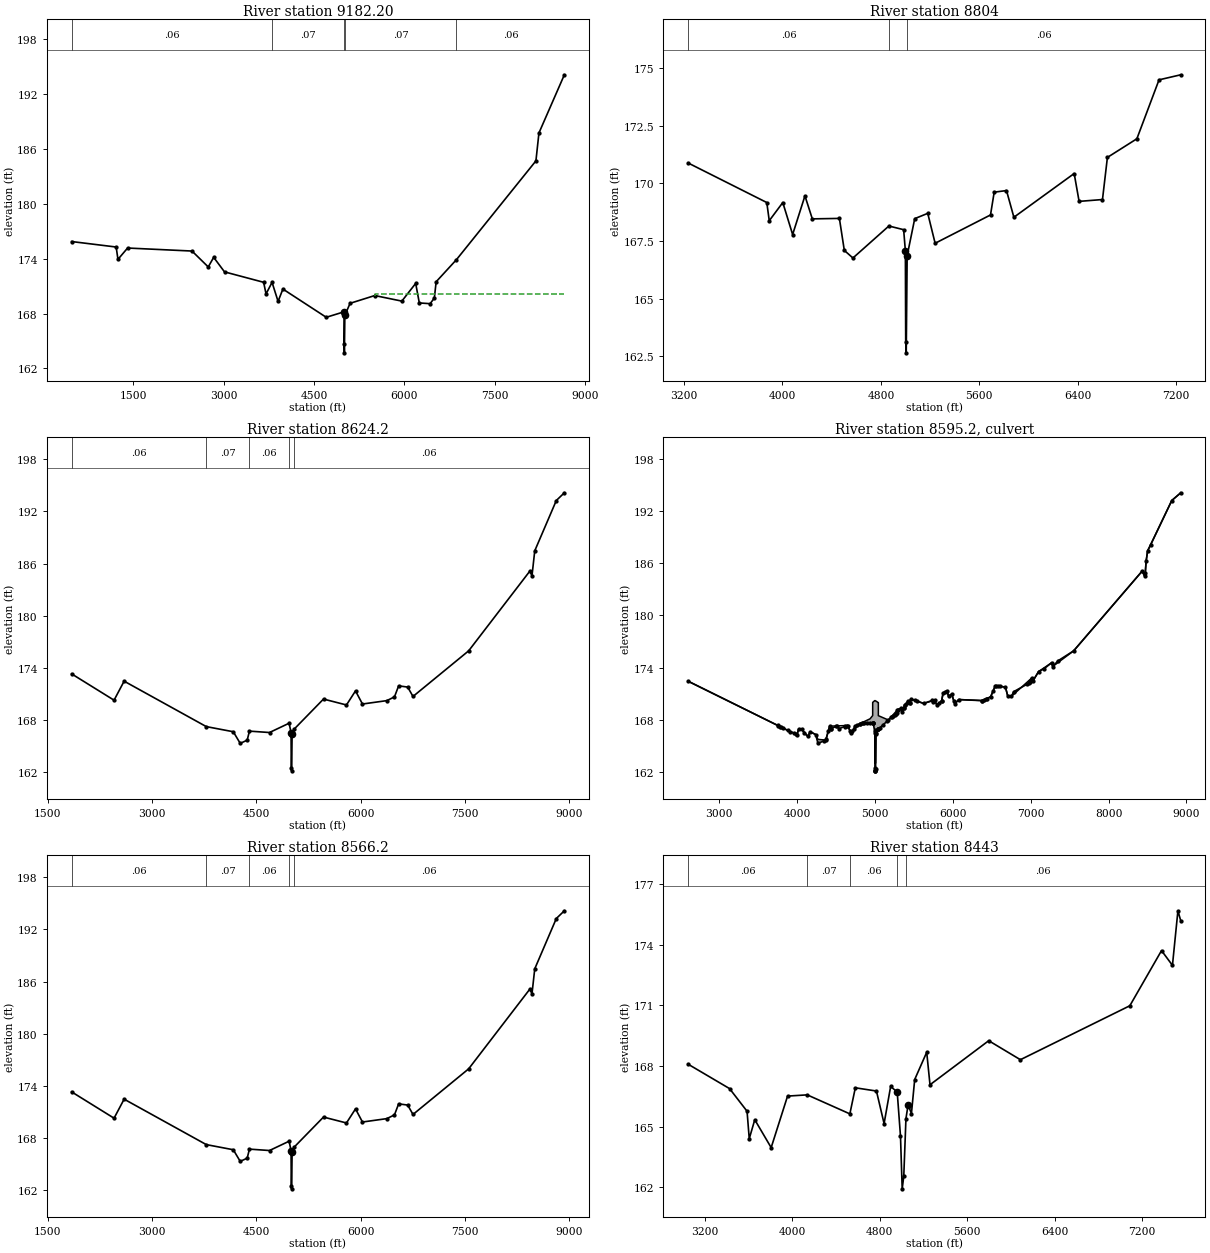
Type RM Length L Ch R = 1 ,9182.20 ,378.2,378.2,378.2
BEGIN DESCRIPTION:
Cross Section K157-00-00-X3A
This has an interpolated channel blended with LIDAR overbanks.
END DESCRIPTION:
XS GIS Cut Line= 4
      2978186.49      13916561.3      2975148.09     13913398.11
      2973402.97      13913117.7       2971503.4     13913840.23
#Sta/Elev= 30
   472.8  175.88  1212.8  175.28  1242.8  173.93  1402.8  175.17  2472.8  174.84
  2742.8   173.1  2832.8  174.15  3012.8  172.56  3662.8  171.42  3702.8  170.15
  3802.8  171.41  3902.8  169.33  3982.8  170.68  4702.8  167.59  4998.9  168.19
 4999.81  164.71 5004.33   163.7 5011.99   167.8  5098.9  169.12  5508.9  169.97
  5958.9  169.36  6188.9   171.3  6248.9  169.16  6428.9  169.08  6498.9   169.7
  6528.9  171.48  6866.4   173.9  8186.4  184.71  8236.4  187.76  8658.7  194.13
#Mann= 5 ,-1 , 0
   472.8     .06       0  3802.8     .07       0  4998.9     .07       0
 5011.99     .07       0  6866.4     .06       0
#XS Ineff= 2 , 0
       0                 5508.85       0   170.1
Permanent Ineff=
       F       F
Bank Sta=4998.9,5011.99
Exp/Cntr=0.3,0.1

Type RM Length L Ch R = 1 ,8804    ,179.8,179.8,179.8
BEGIN DESCRIPTION:
K157-00-00-S2_JACK RD -US - XS4
END DESCRIPTION:
XS GIS Cut Line= 5
      2976468.03      13914159.9      2975299.02     13913093.81
      2974984.57     13912975.89      2973475.13     13912961.14
      2972956.01     13913212.42
#Sta/Elev= 30
  3232.8  170.89  3872.8  169.17  3892.8  168.38  4002.8  169.17  4082.8  167.78
  4182.8  169.46  4242.8  168.46  4462.8  168.48  4502.8  167.09  4572.8  166.76
    4865  168.15    4985  167.99 4998.97  167.07 5001.67  163.11    5006  162.64
 5013.49  166.86    5075  168.47  5180.8   168.7  5240.8   167.4  5690.8  168.63
  5720.8  169.62  5820.8  169.69  5880.8  168.53  6370.8  170.43  6410.8  169.22
  6600.8   169.3  6640.8  171.13  6880.3  171.94  7060.3   174.5  7237.1  174.72
#Mann= 3 ,-1 , 0
  3232.8     .06       0    4865     .07       0 5013.49     .06       0
#XS Ineff= 2 , 0
       0    4890     167    5119       0     167
Permanent Ineff=
       F       F
Bank Sta=4998.97,5013.49
Exp/Cntr=0.5,0.3

Type RM Length L Ch R = 1 ,8624.2  ,58,58,58
BEGIN DESCRIPTION:
K157-00-00-S2_JACK RD -US - XS3
END DESCRIPTION:
XS GIS Cut Line= 6
      2977207.32     13914679.57      2976530.24     13912981.65
      2975519.91     13912872.95      2974863.69     13912868.97
      2973457.32     13912856.65      2971498.99     13913804.57
#Sta/Elev= 30
  1844.6   173.3  2454.6  170.27  2599.4  172.46  3780.7  167.23  4168.3  166.64
  4268.3   165.3  4368.3  165.67  4400.7  166.71  4689.1  166.55 4970.81  167.62
    4999  166.54    5002  162.51  5006.8  162.14  5014.2  166.42    5041  166.92
  5465.3   170.4  5795.3  169.72  5925.3  171.34  6025.3  169.83  6375.3  170.22
  6485.3  170.65  6545.3  171.92  6675.3  171.78  6751.8   170.7  7551.8  175.95
  8431.8  185.13  8461.8  184.57  8501.8  187.46  8811.8  193.25  8927.4  194.14
#Mann= 5 ,-1 , 0
  1844.6     .06       0  3780.7     .07       0  4400.7     .06       0
 4970.81     .07       0    5041     .06       0
#XS Ineff= 2 , 0
       0    4999  166.54  5014.2       0  166.42
Permanent Ineff=
       F       F
Bank Sta=4999,5014.2
Exp/Cntr=0.5,0.3

Type RM Length L Ch R = 2 ,8595.2  ,,,
BEGIN DESCRIPTION:
JACK RD.
Structure ID: K157-00-00-S2
END DESCRIPTION:
Bridge Culvert--1,0,-1,-1, 0
Deck Dist Width WeirC Skew NumUp NumDn MinLoCord MaxHiCord MaxSubmerge Is_Ogee
10,38,3,0, 60, 60, , , 0.95, 0, 1,1,,
  2599.4  3909.4  3999.4  4019.4  4059.4  4138.3  4168.3  4238.3  4268.3  4368.3
  4418.3  4648.3  4689.1  4811.2    4937 4970.59  4970.7  4978.1    4999    5002
  5006.8  5014.2    5041  5043.5 5043.61  5172.6  5289.1  5329.1  5345.3  5385.3
  5465.3  5625.3  5765.3  5795.3  5855.3  5875.3  5925.3  5945.3  5985.3  6025.3
  6075.3  6375.3  6485.3  6545.3  6675.3  6705.3  6751.8  7011.8  7031.8  7101.8
  7271.8  7281.8  7551.8  8431.8  8461.8  8471.8  8481.8  8501.8  8811.8  8927.4
  172.43  166.64   166.3  166.92  166.92  166.08  166.62  166.29  165.73  165.65
  167.25  167.33  166.53  167.56   168.1  168.47  169.97  170.05   170.2  170.19
  170.16  170.13  169.97  169.96  168.46  167.96  169.13   169.3  168.88  169.71
  170.38  169.87  170.23   169.7  170.14  171.07  171.32  170.69  170.95  169.81
  170.32   170.2  170.63   171.9  171.76  170.73  170.68  172.78   172.5  173.54
  174.57  174.11  175.92   185.1  184.54  184.91  186.21  187.43  193.22  194.11
  172.43  166.63  166.29  166.91  166.91  166.07  166.61  166.28  165.27  165.64
  167.24  167.32  166.52  167.55  167.58  167.59  167.59  167.59  166.51  162.48
  162.11  166.39  166.89  166.91  166.91  167.95  169.12  169.29  168.87   169.7
  170.37  169.86  170.22  169.69  170.13  171.06  171.31  170.68  170.94   169.8
  170.31  170.19  170.62  171.89  171.75  170.72  170.67  172.78   172.5  173.54
  174.57  174.11  175.92   185.1  184.54  184.91  186.21  187.43  193.22  194.11
  2599.4  3909.4  3999.4  4019.4  4059.4  4138.3  4168.3  4238.3  4268.3  4368.3
  4418.3  4648.3  4689.1  4811.2    4937 4970.59  4970.7  4978.1    4999    5002
  5006.8  5014.2    5041  5043.5 5043.61  5172.6  5289.1  5329.1  5345.3  5385.3
  5465.3  5625.3  5765.3  5795.3  5855.3  5875.3  5925.3  5945.3  5985.3  6025.3
  6075.3  6375.3  6485.3  6545.3  6675.3  6705.3  6751.8  7011.8  7031.8  7101.8
  7271.8  7281.8  7551.8  8431.8  8461.8  8471.8  8481.8  8501.8  8811.8  8927.4
  172.43  166.64   166.3  166.92  166.92  166.08  166.62  166.29  165.73  165.65
  167.25  167.33  166.53  167.56   168.1  168.47  169.97  170.05   170.2  170.19
  170.16  170.13  169.97  169.96  168.46  167.96  169.13   169.3  168.88  169.71
  170.38  169.87  170.23   169.7  170.14  171.07  171.32  170.69  170.95  169.81
  170.32   170.2  170.63   171.9  171.76  170.73  170.68  172.78   172.5  173.54
  174.57  174.11  175.92   185.1  184.54  184.91  186.21  187.43  193.22  194.11
  172.43  166.63  166.29  166.91  166.91  166.07  166.61  166.28  165.27  165.64
  167.24  167.32  166.52  167.55  167.58  167.59  167.59  167.59  166.51  162.48
  162.11  166.39  166.89  166.91  166.91  167.95  169.12  169.29  168.87   169.7
  170.37  169.86  170.22  169.69  170.13  171.06  171.31  170.68  170.94   169.8
  170.31  170.19  170.62  171.89  171.75  170.72  170.67  172.78   172.5  173.54
  174.57  174.11  175.92   185.1  184.54  184.91  186.21  187.43  193.22  194.11
BR Coef= 1 , 0 , 0 ,1.25, 0 ,,,0.8,0,2,0,
WSPro=,,,, 1 ,,,, 0 ,,,, 0 ,,,,-1 ,-1 ,-1 , 0 , 0 , 0 , 0 , 0
Culvert=1,4,,38,0.012,0.2,1,1,3,162.91,5002.1,162.86,5002.1,Culvert #1  , 0 ,10
Culvert Bottom n=0.012
Culvert=1,4,,38,0.012,0.2,1,1,3,162.96,5007.4,162.68,5007.4,Culvert #2  , 0 ,10
Culvert Bottom n=0.012
BR U #Sta/Elev= 139
  2599.4  172.43  3750.7  167.33  3760.7  167.29  3780.7   167.2  3790.7  167.16
  3820.7  167.02  3880.7  166.76  3909.4  166.63  3960.7  166.44  3980.7  166.36
  3999.4  166.29  4019.4  166.91  4059.4  166.91  4088.3  166.48  4138.3  166.07
  4168.3  166.61  4238.3  166.28  4268.3  165.27  4350.7  165.57  4368.3  165.64
  4370.7  165.72  4400.7  166.68  4418.3  167.24  4438.3  166.97  4440.7  166.98
  4500.7  167.24  4518.3  167.31  4538.3  166.97  4610.7   167.2  4620.7  167.23
  4640.7   167.3  4648.3  167.32  4680.7  166.68  4689.1  166.52  4710.7  166.71
  4729.1  166.88  4739.1  167.23  4770.7  167.37  4802.6  167.51  4811.2  167.55
  4832.6  167.56  4852.6  167.56  4855.4  167.56  4893.5  167.57    4937  167.58
 4970.59  167.59  4970.7  167.59 4970.81  167.59  4978.1  167.59  4994.8  166.73
    4999  166.51    5002  162.48  5003.2  162.21    5005  162.14  5005.1  162.14
  5006.8  162.11  5007.6  162.33  5014.2  166.39  5016.9  166.44    5041  166.89
 5043.39  166.91  5043.5  166.91 5043.61  166.91  5058.9  167.03  5106.5  167.42
  5152.1  167.79  5172.6  167.95  5211.8  168.27  5219.1  168.31    5235  168.43
    5255  168.57    5265  168.65  5279.1  168.75  5289.1  169.12    5295  169.15
  5329.1  169.29  5345.3  168.87    5375  169.29  5375.3  169.29    5385  169.69
  5385.3   169.7    5405  169.91  5425.3  170.13    5445  169.86  5445.3  169.86
  5465.3  170.37    5515  170.21    5545  170.12  5625.3  169.86  5735.3  170.22
  5745.3     170  5765.3  170.22  5795.3  169.69    5825  169.91    5855  170.13
  5855.3  170.13  5875.3  171.06    5895  171.16  5925.3  171.31  5945.3  170.68
  5985.3  170.94    6015  170.09  6025.3   169.8  6075.3  170.31    6375  170.19
  6375.3  170.19    6395  170.27    6425  170.38    6435  170.42  6485.3  170.62
    6515  171.25  6545.3  171.89    6555  171.88    6585  171.85    6605  171.83
  6675.3  171.75  6705.3  170.72  6751.8  170.67  6781.8  171.22    6955  172.09
  6981.8  172.22    6985  172.28  6992.9  172.43  7011.8  172.78  7031.8   172.5
  7101.8  173.54  7171.8  173.86  7271.8  174.57  7281.8  174.11  7351.8  174.78
  7551.8  175.92  8431.8   185.1  8461.8  184.54  8471.8  184.91  8481.8  186.21
  8501.8  187.43  8541.8  188.14  8811.8  193.22  8927.4  194.11
BR U #Mann= 5
  2599.4     .06  3780.7     .07  4400.7     .06 4970.81     .07    5041     .06
BR U Banks=4999,5014.2
BR D #Sta/Elev= 139
  2599.4  172.43  3750.7  167.33  3760.7  167.29  3780.7   167.2  3790.7  167.16
  3820.7  167.02  3880.7  166.76  3909.4  166.63  3960.7  166.44  3980.7  166.36
  3999.4  166.29  4019.4  166.91  4059.4  166.91  4088.3  166.48  4138.3  166.07
  4168.3  166.61  4238.3  166.28  4268.3  165.27  4350.7  165.57  4368.3  165.64
  4370.7  165.72  4400.7  166.68  4418.3  167.24  4438.3  166.97  4440.7  166.98
  4500.7  167.24  4518.3  167.31  4538.3  166.97  4610.7   167.2  4620.7  167.23
  4640.7   167.3  4648.3  167.32  4680.7  166.68  4689.1  166.52  4710.7  166.71
  4729.1  166.88  4739.1  167.23  4770.7  167.37  4802.6  167.51  4811.2  167.55
  4832.6  167.56  4852.6  167.56  4855.4  167.56  4893.5  167.57    4937  167.58
 4970.59  167.59  4970.7  167.59 4970.81  167.59  4978.1  167.59  4994.8  166.73
    4999  166.51    5002  162.48  5003.2  162.21    5005  162.14  5005.1  162.14
  5006.8  162.11  5007.6  162.33  5014.2  166.39  5016.9  166.44    5041  166.89
 5043.39  166.91  5043.5  166.91 5043.61  166.91  5058.9  167.03  5106.5  167.42
  5152.1  167.79  5172.6  167.95  5211.8  168.27  5219.1  168.31    5235  168.43
    5255  168.57    5265  168.65  5279.1  168.75  5289.1  169.12    5295  169.15
  5329.1  169.29  5345.3  168.87    5375  169.29  5375.3  169.29    5385  169.69
  5385.3   169.7    5405  169.91  5425.3  170.13    5445  169.86  5445.3  169.86
  5465.3  170.37    5515  170.21    5545  170.12  5625.3  169.86  5735.3  170.22
  5745.3     170  5765.3  170.22  5795.3  169.69    5825  169.91    5855  170.13
  5855.3  170.13  5875.3  171.06    5895  171.16  5925.3  171.31  5945.3  170.68
  5985.3  170.94    6015  170.09  6025.3   169.8  6075.3  170.31    6375  170.19
  6375.3  170.19    6395  170.27    6425  170.38    6435  170.42  6485.3  170.62
    6515  171.25  6545.3  171.89    6555  171.88    6585  171.85    6605  171.83
  6675.3  171.75  6705.3  170.72  6751.8  170.67  6781.8  171.22    6955  172.09
  6981.8  172.22    6985  172.28  6992.9  172.43  7011.8  172.78  7031.8   172.5
  7101.8  173.54  7171.8  173.86  7271.8  174.57  7281.8  174.11  7351.8  174.78
  7551.8  175.92  8431.8   185.1  8461.8  184.54  8471.8  184.91  8481.8  186.21
  8501.8  187.43  8541.8  188.14  8811.8  193.22  8927.4  194.11
BR D #Mann= 5
  2599.4     .06  3780.7     .07  4400.7     .06 4970.81     .07    5041     .06
BR D Banks=4999,5014.2
BC Design=,, 0 ,, 0 ,,,,,,
BC HTab HWMax=194.14

Type RM Length L Ch R = 1 ,8566.2  ,123.2,123.2,123.2
BEGIN DESCRIPTION:
K157-00-00-S2_JACK RD -DS - XS2
END DESCRIPTION:
XS GIS Cut Line= 6
      2977231.19     13914638.89      2976549.65     13912929.79
      2975526.34     13912819.68      2974869.13     13912815.69
      2973458.11     13912803.34      2971495.57      13913753.3
#Sta/Elev= 30
  1844.6   173.3  2454.6  170.27  2599.4  172.46  3780.7  167.23  4168.3  166.64
  4268.3   165.3  4368.3  165.67  4400.7  166.71  4689.1  166.55 4970.81  167.62
    4999  166.54    5002  162.51  5006.8  162.14  5014.2  166.42    5041  166.92
  5465.3   170.4  5795.3  169.72  5925.3  171.34  6025.3  169.83  6375.3  170.22
  6485.3  170.65  6545.3  171.92  6675.3  171.78  6751.8   170.7  7551.8  175.95
  8431.8  185.13  8461.8  184.57  8501.8  187.46  8811.8  193.25  8927.4  194.14
#Mann= 5 ,-1 , 0
  1844.6     .06       0  3780.7     .07       0  4400.7     .06       0
 4970.81     .07       0    5041     .06       0
#XS Ineff= 2 , 0
       0  4990.1     166  5019.4       0     166
Permanent Ineff=
       F       F
Bank Sta=4999,5014.2
Exp/Cntr=0.5,0.3

Type RM Length L Ch R = 1 ,8443    ,1261,1261,1261
BEGIN DESCRIPTION:
K157-00-00-S2_JACK RD -DS - XS1
END DESCRIPTION:
XS GIS Cut Line= 6
      2976984.02      13913355.7      2976588.25     13912890.76
      2975561.43     13912706.73      2974904.21     13912702.74
       2973493.2     13912690.39       2972707.6     13912658.63
#Sta/Elev= 30
  3046.8  168.09  3426.8  166.88  3586.8  165.76  3606.8   164.4  3657.4  165.34
  3807.4  163.96  3957.4  166.51  4137.4  166.57  4527.4  165.63  4577.4  166.92
  4770.6  166.76  4840.6  165.15  4900.6  166.99  4960.6  166.71  4990.6  164.53
 5006.19  161.92  5020.6  162.54  5040.6   165.4  5060.6  166.09  5090.6  165.64
  5120.6  167.33  5230.6  168.68  5260.6  167.07  5797.8  169.25  6087.8  168.31
  7088.9  170.98  7378.9  173.71  7478.9  172.98  7528.9  175.68  7555.1  175.18
#Mann= 5 ,-1 , 0
  3046.8     .06       0  4137.4     .07       0  4527.4     .06       0
  4960.6     .07       0  5040.6     .06       0
#XS Ineff= 2 , 0
       0    4890     166    5119       0     166
Permanent Ineff=
       F       F
Bank Sta=4960.6,5060.6
Exp/Cntr=0.3,0.1

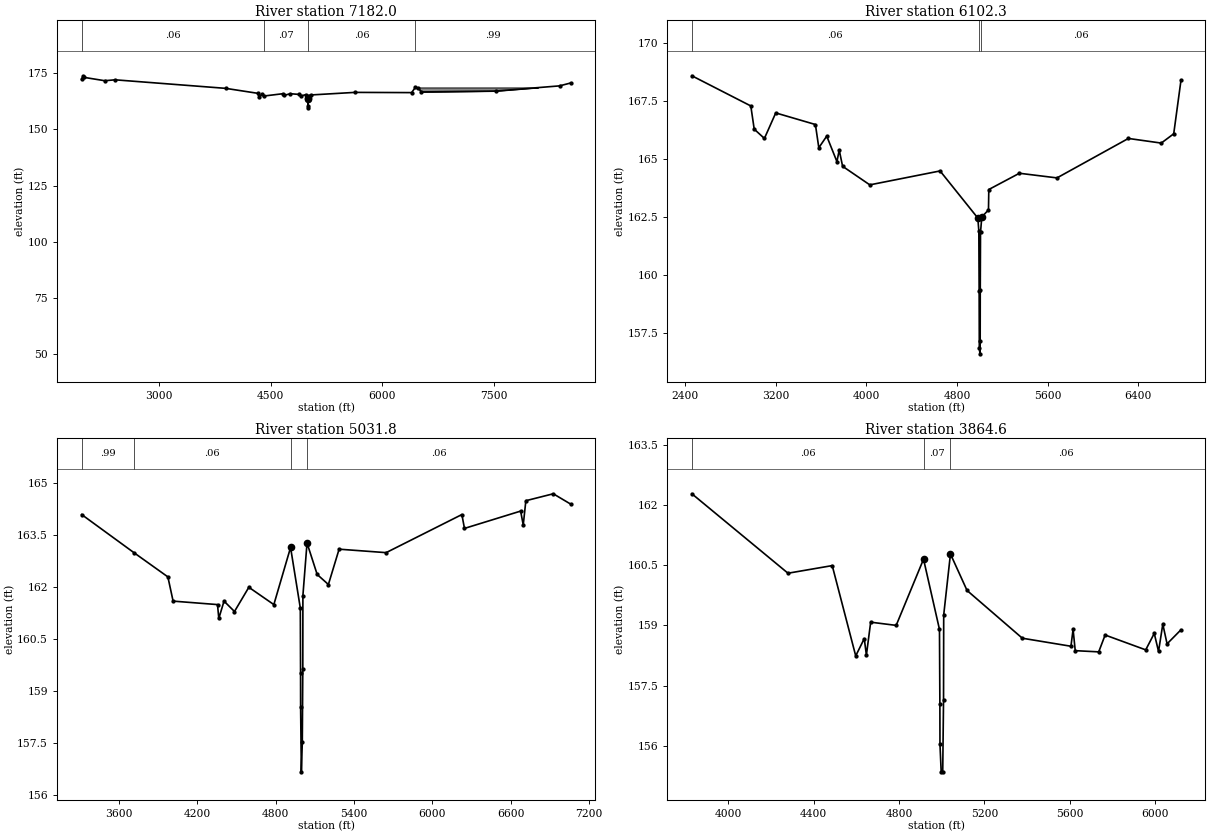
Type RM Length L Ch R = 1 ,7182.0  ,1032,1079.7,928
BEGIN DESCRIPTION:
Cross Section K157-00-00-X03
END DESCRIPTION:
XS GIS Cut Line= 5
      2977698.84     13914945.22      2977599.86     13913833.34
      2976638.77     13912858.13      2975411.18     13911620.93
      2973063.42      13911494.7
#Sta/Elev= 30
  1955.4   172.4  1975.4   173.9  1985.4   173.2  2265.4   171.7  2405.4   172.1
  3891.7   168.3  4321.7   166.1  4341.7   164.5  4381.7   165.8  4411.7   164.9
  4660.9   165.9  4680.9   165.2  4760.9   165.9  4880.9   165.6  4900.9   164.9
  4970.6  165.48  4996.5  163.98    5000  159.63  5000.8   160.5  5001.7   163.5
  5014.7  164.75  5042.4  165.36  5630.9   166.5  6393.8   166.4  6443.8   168.7
  6483.8   168.5  6523.8   166.7  7523.8   167.1  8383.8   169.4  8534.9   170.7
#Mann= 4 ,-1 , 0
  1955.4     .06       0  4411.7     .07       0  5001.7     .06       0
  6443.8     .99       0
#Block Obstruct= 2 ,-1
    6470    8096   168.7    9000    9001      50
Bank Sta=4996.5,5001.7
Exp/Cntr=0.3,0.1

Type RM Length L Ch R = 1 ,6102.3  ,1294,1070.5,1066
BEGIN DESCRIPTION:
Cross Section K157-00-00-X02
END DESCRIPTION:
XS GIS Cut Line= 6
       2978740.5     13913356.68      2977077.91     13911877.26
      2976961.76     13911717.05      2976793.53     13911615.32
      2976417.18     13911448.45      2975138.08     13911337.87
#Sta/Elev= 30
  2460.3   168.6  2980.3   167.3  3010.3   166.3  3100.3   165.9  3200.3     167
  3550.3   166.5  3580.3   165.5  3650.3     166  3740.3   164.9  3760.3   165.4
  3790.3   164.7  4030.3   163.9  4650.3   164.5  4983.6  162.47  4992.4  161.91
  4995.1  159.33  4996.5  156.89  5002.2  156.62  5004.2  157.17  5004.9  159.37
  5007.1  161.85  5018.7  162.52  5077.5  162.82  5080.3   163.7  5350.3   164.4
    5682   164.2    6312   165.9    6602   165.7    6712   166.1  6775.9   168.4
#Mann= 3 ,-1 , 0
  2460.3     .06       0  4992.4     .07       0  5007.1     .06       0
Bank Sta=4983.6,5018.7
Exp/Cntr=0.3,0.1

Type RM Length L Ch R = 1 ,5031.8  ,590.3,1167.2,1765.9
BEGIN DESCRIPTION:
Cross Section K157-00-00-X01 **SEE NOTE**
This cross section cannot be extended.  This is an overflow to K100-00-00.
END DESCRIPTION:
XS GIS Cut Line= 5
 2979073.111736513911701.0779416      2978735.29     13911486.89
      2977914.93     13910966.76      2977334.61     13911118.36
      2975576.44     13910882.72
#Sta/Elev= 30
  3315.5   164.1  3715.5     163  3975.5   162.3  4015.5   161.6  4355.5   161.5
  4365.5   161.1  4405.5   161.6  4485.5   161.3  4595.5     162  4786.9   161.5
    4915  163.15  4989.6   161.4  4991.5  159.53  4991.9  158.54  4997.6  156.67
  5004.8  157.52  5008.6  159.64  5009.4  161.76    5041  163.28  5118.7  162.37
  5204.6  162.08  5286.6   163.1  5646.6     163  6226.6   164.1  6246.6   163.7
  6676.6   164.2  6696.6   163.8  6716.6   164.5  6926.6   164.7  7060.5   164.4
#Mann= 4 ,-1 , 0
  3315.5     .99       0  3715.5     .06       0    4915     .07       0
    5041     .06       0
Bank Sta=4915,5041
Exp/Cntr=0.3,0.1

Type RM Length L Ch R = 1 ,3864.6  ,0,0,0
BEGIN DESCRIPTION:
Cross Section K157-00-00-X01a **SEE NOTE**
Interpolated 1 cross-section
This cross section cannot be extended.  This is an overflow to K100-00-00.
END DESCRIPTION:
XS GIS Cut Line= 4
    2978695.1417      13911372.9       2978597.2      13910723.2
      2977980.88      13909863.8      2977703.11      13909360.3
#Sta/Elev= 30
  3830.5  162.28  4280.5   160.3  4487.5  160.49  4597.5  158.24  4637.5  158.67
  4647.5  158.26  4667.5  159.08  4786.9     159    4915  160.65  4989.6   158.9
  4991.5  157.03  4991.9  156.04  4997.6  155.35  5004.8  155.35  5008.6  157.14
  5009.4  159.26    5041  160.78  5118.7  159.87  5377.5  158.68  5605.1  158.48
  5615.1   158.9  5625.1  158.37  5735.1  158.34  5765.1  158.76  5955.1  158.39
  5995.1   158.8  6015.1  158.35  6035.1  159.03  6055.1  158.54  6120.1  158.89
#Mann= 3 ,-1 , 0
  3830.5     .06       0    4915     .07       0    5041     .06       0
Bank Sta=4915,5041
Exp/Cntr=0.3,0.1

Chan Stop Cuts=-1
Use User Specified Reach Order=0
User Specified Reach Order=K157-00-00      ,K157-00-00_0039